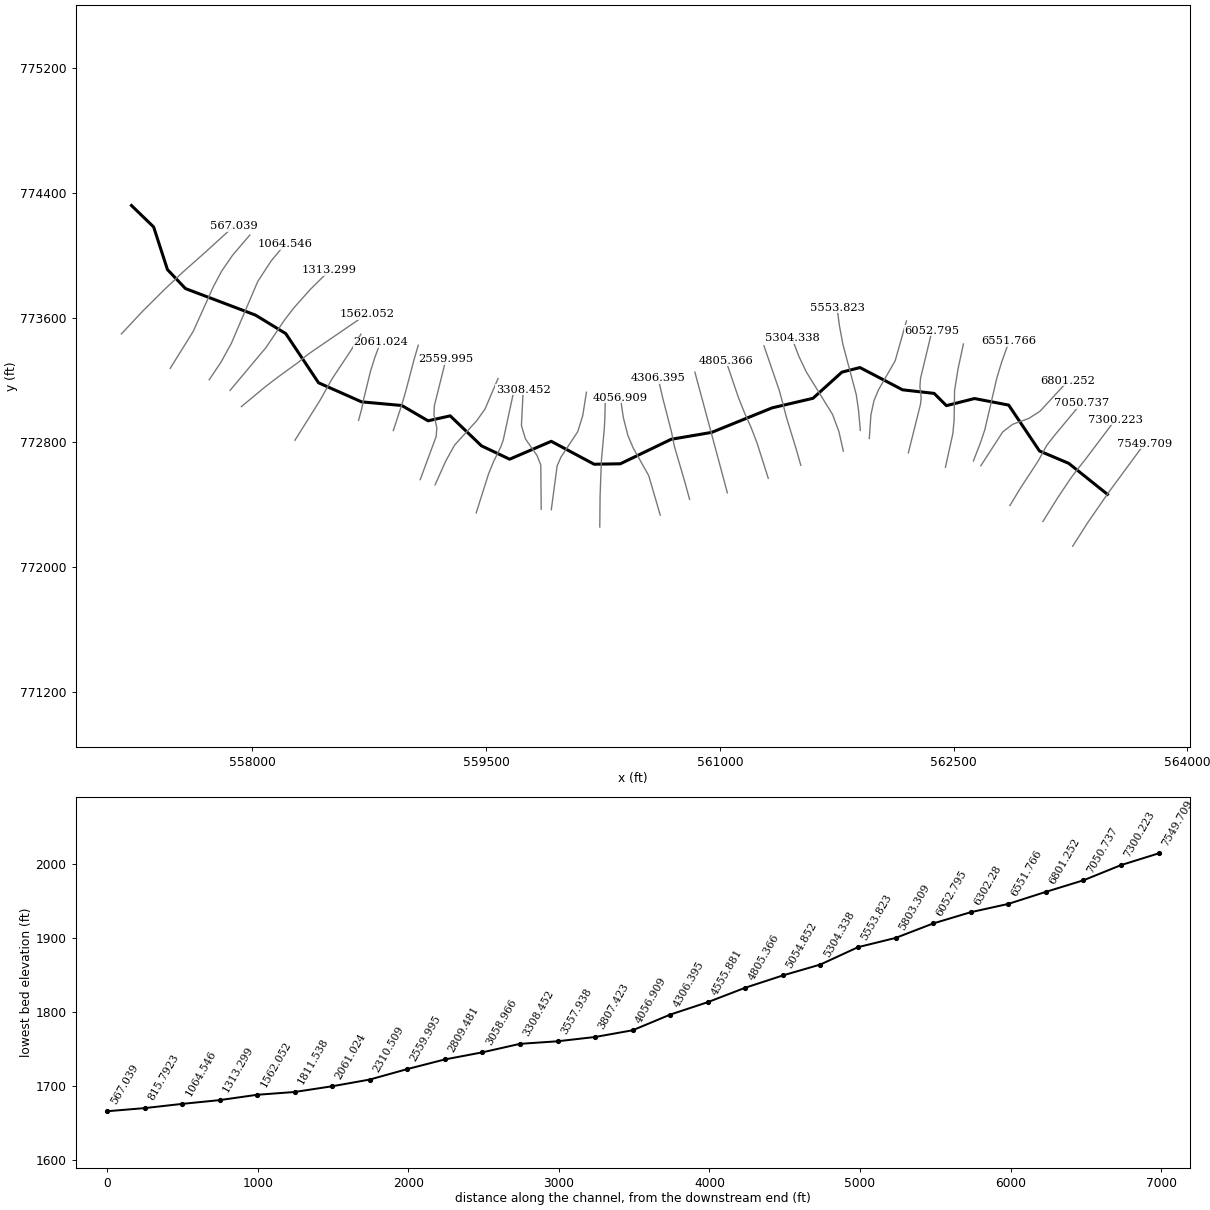
--- 10883_ras.prj (project) ---

Proj Title=10883
Current Plan=p01
Default Exp/Contr=0.3,0.1
English Units
Geom File=g01
Flow File=f01
Plan File=p01
Y Axis Title=Elevation
X Axis Title(PF)=Main Channel Distance
X Axis Title(XS)=Station
BEGIN DESCRIPTION:
RFD model 10883 exported to HEC-RAS
END DESCRIPTION:

--- 10883_ras.p01 (plan) ---

Plan Title=Plan 01
Program Version=4.10
Short Identifier=Plan 01
Geom File=g01
Flow File=f01
Subcritical Flow
Calc Critical at every XS
Secant Critical Depth

--- 10883_ras.f01 (steady flow) ---

Flow Title=Flow 01
Program Version=5.01
Number of Profiles= 6
Profile Names=10yr,25yr,50yr,100yr,100plus,500yr
River Rch & RM=10883,29,7549.709
  1371.9 2134.82  2835.2 3443.04 5026.84 6280.19
River Rch & RM=10883,29,7300.223
 1390.92 2165.08    2876 3493.19 5100.06 6361.03
River Rch & RM=10883,29,7050.737
 1401.05 2181.17 2897.67 3519.81 5138.92 6403.74
River Rch & RM=10883,29,6801.252
 1407.67  2191.7 2911.86 3537.24 5164.37 6431.74
River Rch & RM=10883,29,6551.766
 1415.33 2203.92 2928.37 3557.57 5194.06 6464.56
River Rch & RM=10883,29, 6302.28
 1433.74  2233.3 2968.06 3606.44  5265.4 6543.29
River Rch & RM=10883,29,6052.795
 1466.91 2286.17 3039.41 3694.23 5393.58 6684.07
River Rch & RM=10883,29,5803.309
 1471.33 2293.25 3049.02 3706.09 5410.89 6703.23
River Rch & RM=10883,29,5553.823
 1724.69 2697.48  3595.1 4378.41 6392.48 7767.46
River Rch & RM=10883,29,5304.338
 1740.54 2722.97 3629.72 4421.22 6454.98 7835.12
River Rch & RM=10883,29,5054.852
 1758.27 2751.33  3668.1 4468.55 6524.08 7909.29
River Rch & RM=10883,29,4805.366
 1761.82 2757.11    3676 4478.37 6538.42 7924.98
River Rch & RM=10883,29,4555.881
    1775  2778.4    3705 4514.34 6590.94 7982.06
River Rch & RM=10883,29,4306.395
 1786.53 2797.08 3730.47 4545.96  6637.1 8032.29
River Rch & RM=10883,29,4056.909
 1795.19 2811.12 3749.64 4569.77 6671.86 8070.16
River Rch & RM=10883,29,3807.423
  1814.7 2842.79 3792.89 4623.53 6750.35 8155.67
River Rch & RM=10883,29,3557.938
 1825.56 2860.42 3816.97 4653.47 6794.07 8203.27
River Rch & RM=10883,29,3308.452
 1829.82 2867.36 3826.46 4665.28 6811.31 8222.06
River Rch & RM=10883,29,3058.966
 1851.49 2902.54 3874.52 4725.03 6898.54 8316.85
River Rch & RM=10883,29,2809.481
 1865.37 2925.29 3905.77 4764.07 6955.55 8379.44
River Rch & RM=10883,29,2559.995
 1870.65 2933.97 3917.73 4779.05 6977.41 8403.55
River Rch & RM=10883,29,2310.509
 1920.23  3014.8 4028.44    4917 7178.82 8622.58
River Rch & RM=10883,29,2061.024
 1922.37 3018.33  4033.3 4923.09 7187.71 8632.33
Boundary for River Rch & Prof#=10883,29,1
Up Type= 0
Dn Type= 2
Boundary for River Rch & Prof#=10883,29,2
Up Type= 0
Dn Type= 2
Boundary for River Rch & Prof#=10883,29,2
Up Type= 0
Dn Type= 2
Boundary for River Rch & Prof#=10883,29,2
Up Type= 0
Dn Type= 2
Boundary for River Rch & Prof#=10883,29,2
Up Type= 0
Dn Type= 2
Boundary for River Rch & Prof#=10883,29,2
Up Type= 0
Dn Type= 2

--- 10883_ras.g01 (geometry) ---

Geom Title=10883
Program Version=4.10

River Reach=10883,29
Reach XY= 30
563486.784934938772465.887009412563238.319371581772664.623994842
563050.671986967772744.050145149562853.009670466773038.408858791
562633.598399401773080.527543232 562453.31583637773034.880702019
562374.886415988773113.475196376562172.249696821773136.440694362
561898.933755487773279.282952547561782.855873466773249.741869554
561597.405864716773081.986900419561334.890632451773020.565781102
560947.366749734772863.257796749560687.819885135772819.086558148
560361.356241703772661.858561918560193.386734426772658.998104095
559918.161899656772806.039033398559650.995782822772691.309559345
559470.335892439772777.125838101559269.694317609772969.451557189
559127.866147697772937.603629291558959.485213995773035.767325997
558701.538305372773059.158333957558425.192848057773181.428025469
558214.755150884773497.211594701558020.719321489773615.715202689
557571.173534691773786.048917875557455.747487158773907.700815782
557367.096590966774181.297768533557224.694591165774319.184670106

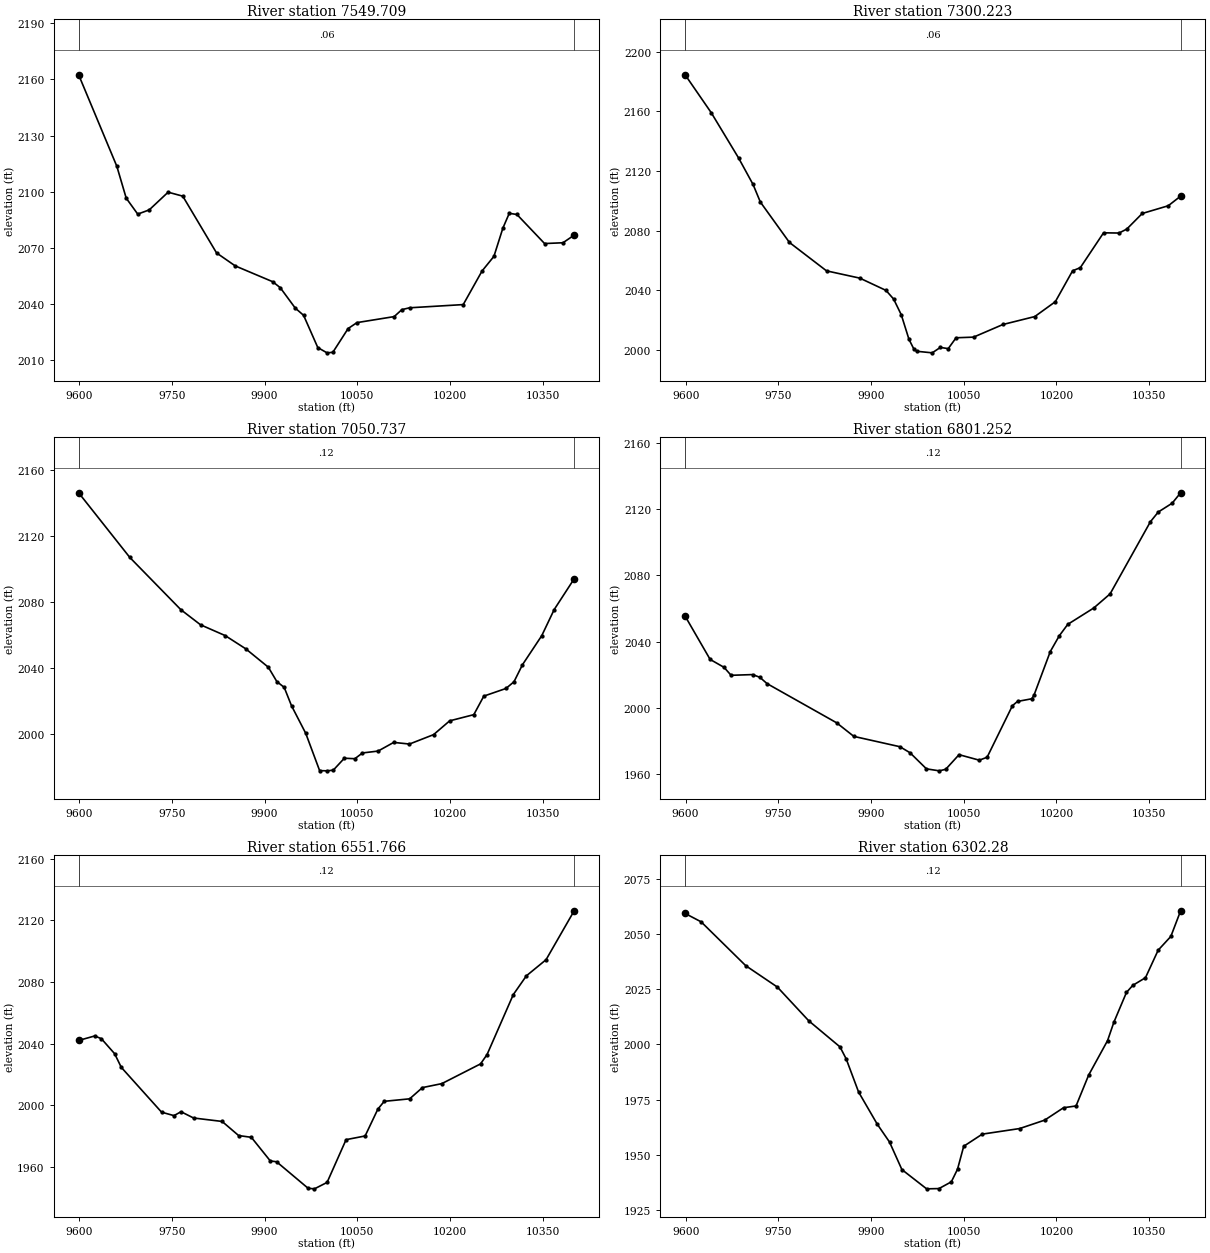
Type RM Length L Ch R = 1 ,7549.709,249.485700,249.485700,249.485700
XS GIS Cut Line= 6
563263.642968924772132.831069753563357.433671281772280.176619211
563485.393165786 772465.63605398563486.533979506772467.278778564
563493.920599158772477.870429924563723.384842482772789.597978787
#Sta/Elev= 30
9599.017 2162.429660.8582113.5679676.035 2096.559694.6582088.047 9713.282090.299
9743.8362099.7489767.544 2097.639822.2212067.3289852.4362060.4069913.182 2051.95
9925.3322048.763 9949.632037.864 9963.092034.0219986.0782016.809   100012013.995
10010.41 2014.2710035.182026.97110049.472030.12910109.692033.338 10122.12037.053
10134.522038.03710221.44 2039.75 10251.92057.67510271.112065.48910285.632080.579
10295.942088.46910308.362087.84510353.112072.33110382.862072.75410400.992076.822
#Mann= 3 , 0 , 0
9599.017    0.06       09599.017    0.06       010400.99    0.06       0
#XS Ineff= 2 , 0
       0                               0
Bank Sta=9599.017,10400.99
Exp/Cntr=0.3,0.1

Type RM Length L Ch R = 1 ,7300.223,249.485700,249.485700,249.485700
XS GIS Cut Line= 6
 563072.67117247772291.627943505563165.292437587772440.406986098
  563250.2410512772567.575043477563277.990797241772605.046808015
563348.579829855772694.546831519563537.072709642 772944.63577219
#Sta/Elev= 30
9599.0242184.5179641.2732159.1389685.4522128.8529709.0112111.0019720.7912099.244
9767.9092072.1319827.9052053.1029881.768 2048.239924.1122040.0099936.4482034.244
9948.8922023.6599961.3352007.2069968.8122001.0569973.8371999.206    99991998.158
10012.152001.80410024.862000.96910037.572008.25410065.822008.68110113.442017.156
10164.952022.47210198.182032.42110226.142053.13610238.662055.26410276.232078.601
10301.27 2078.4510313.792081.09310338.842091.55510380.942096.73110400.992103.191
#Mann= 3 , 0 , 0
9599.024    0.06       09599.024    0.06       010400.99    0.06       0
#XS Ineff= 2 , 0
       0                               0
Bank Sta=9599.024,10400.99
Exp/Cntr=0.3,0.1

Type RM Length L Ch R = 1 ,7050.737,249.485600,249.485600,249.485600
XS GIS Cut Line= 6
562860.836465016772394.132221834562928.996782921772506.476499887
563043.881217561772682.398910412563096.235254094772778.362173213
 563143.25199927772839.282188808563318.562673028773049.836098898
#Sta/Elev= 30
9599.0332146.2489681.9242107.0049764.5042075.3419796.2832066.2059836.165 2059.66
9869.4392051.6449906.017 2040.489919.7692031.7829931.7122028.2439943.5412017.097
9966.5472000.393 9989.011977.778   100011977.64110011.111978.04310029.041985.287
10046.031984.994 10058.41988.48810083.661989.62910108.931994.88710134.411993.885
10173.451999.59410199.472007.95410238.512011.70310254.73 2022.9510290.562027.588
10303.572031.66110317.242041.955 10348.52059.60310368.632075.45110400.952094.086
#Mann= 3 , 0 , 0
9599.033    0.12       09599.033    0.12       010400.95    0.12       0
#XS Ineff= 2 , 0
       0                               0
Bank Sta=9599.033,10400.95
Exp/Cntr=0.3,0.1

Type RM Length L Ch R = 1 ,6801.252,249.485700,249.485700,249.485700
XS GIS Cut Line= 6
562674.105159768772649.033789945 562814.89018111772866.452730351
 562878.59277258772915.340322229562981.825789774772952.696747084
563053.678590532772998.729498221563233.438397277 773193.48743934
#Sta/Elev= 30
9599.1782055.4239639.6812029.2779662.2042024.4919673.5832019.6939708.457 2020.13
9720.0822018.4979731.7062014.695 9844.331991.0369872.1721982.8359946.7511976.598
 9963.051972.972 9989.681963.23910010.441962.04810020.841962.98510042.391971.805
10075.151968.47510087.791970.24710128.772001.37910136.962003.92610159.982005.527
10163.492007.54810190.022034.04510204.682043.617 10218.32050.44410260.292060.295
10286.752068.81310351.972112.34210364.682118.20810387.212123.54810400.892129.829
#Mann= 3 , 0 , 0
9599.178    0.12       09599.178    0.12       010400.89    0.12       0
#XS Ineff= 2 , 0
       0                               0
Bank Sta=9599.178,10400.89
Exp/Cntr=0.3,0.1

Type RM Length L Ch R = 1 ,6551.766,249.485700,249.485700,249.485700
XS GIS Cut Line= 6
562626.903073817772680.647794097562672.821371249772799.435193719
562700.259774299772881.374681383562776.797367275773211.593381196
 562807.20677401773311.711001907562855.597116708773447.859019481
#Sta/Elev= 30
9599.0312042.0889625.1392045.012 9635.862043.2129657.303 2033.489668.0242024.651
9733.2461995.5339753.3451993.2849764.7381995.8229784.9821991.7549831.2331989.512
9857.9391980.3619878.5461979.2039909.1881963.8869919.4021963.3259970.4711946.112
9980.6851945.76310001.121949.94110031.851977.69310062.661980.08510083.261997.493
10093.562002.57310134.752004.196 10155.42011.48410186.762014.05810249.462026.873
10259.972032.92110302.422071.83310323.652084.04410355.482094.50210400.972126.266
#Mann= 3 , 0 , 0
9599.031    0.12       09599.031    0.12       010400.97    0.12       0
#XS Ineff= 2 , 0
       0                               0
Bank Sta=9599.031,10400.97
Exp/Cntr=0.3,0.1

Type RM Length L Ch R = 1 , 6302.28,249.485700,249.485700,249.485700
XS GIS Cut Line= 6
562447.249025194772639.858763034562494.648512163772854.707625088
562502.931936152772941.836685825562505.806407159773131.198491696
562527.493153505773267.819592961562562.553296623773430.448973662
#Sta/Elev= 30
9599.0442059.1999624.974  2055.49697.1692035.5559748.3882025.8749799.1922010.599
9849.6911998.8149859.7621993.357 9879.831978.3699909.8951963.8849929.8951955.736
9949.8951943.2829989.8961934.574 10009.91934.693 10029.91937.745 10039.91943.444
10049.911953.83210079.991959.32710140.481961.85610180.981965.66710211.431971.273
10231.721972.07810252.111986.04710282.722001.65710292.922009.96410313.322023.464
10323.562026.65810344.082030.113 10364.62042.56910385.122048.78810400.972060.398
#Mann= 3 , 0 , 0
9599.044    0.12       09599.044    0.12       010400.97    0.12       0
#XS Ineff= 2 , 0
       0                               0
Bank Sta=9599.044,10400.97
Exp/Cntr=0.3,0.1

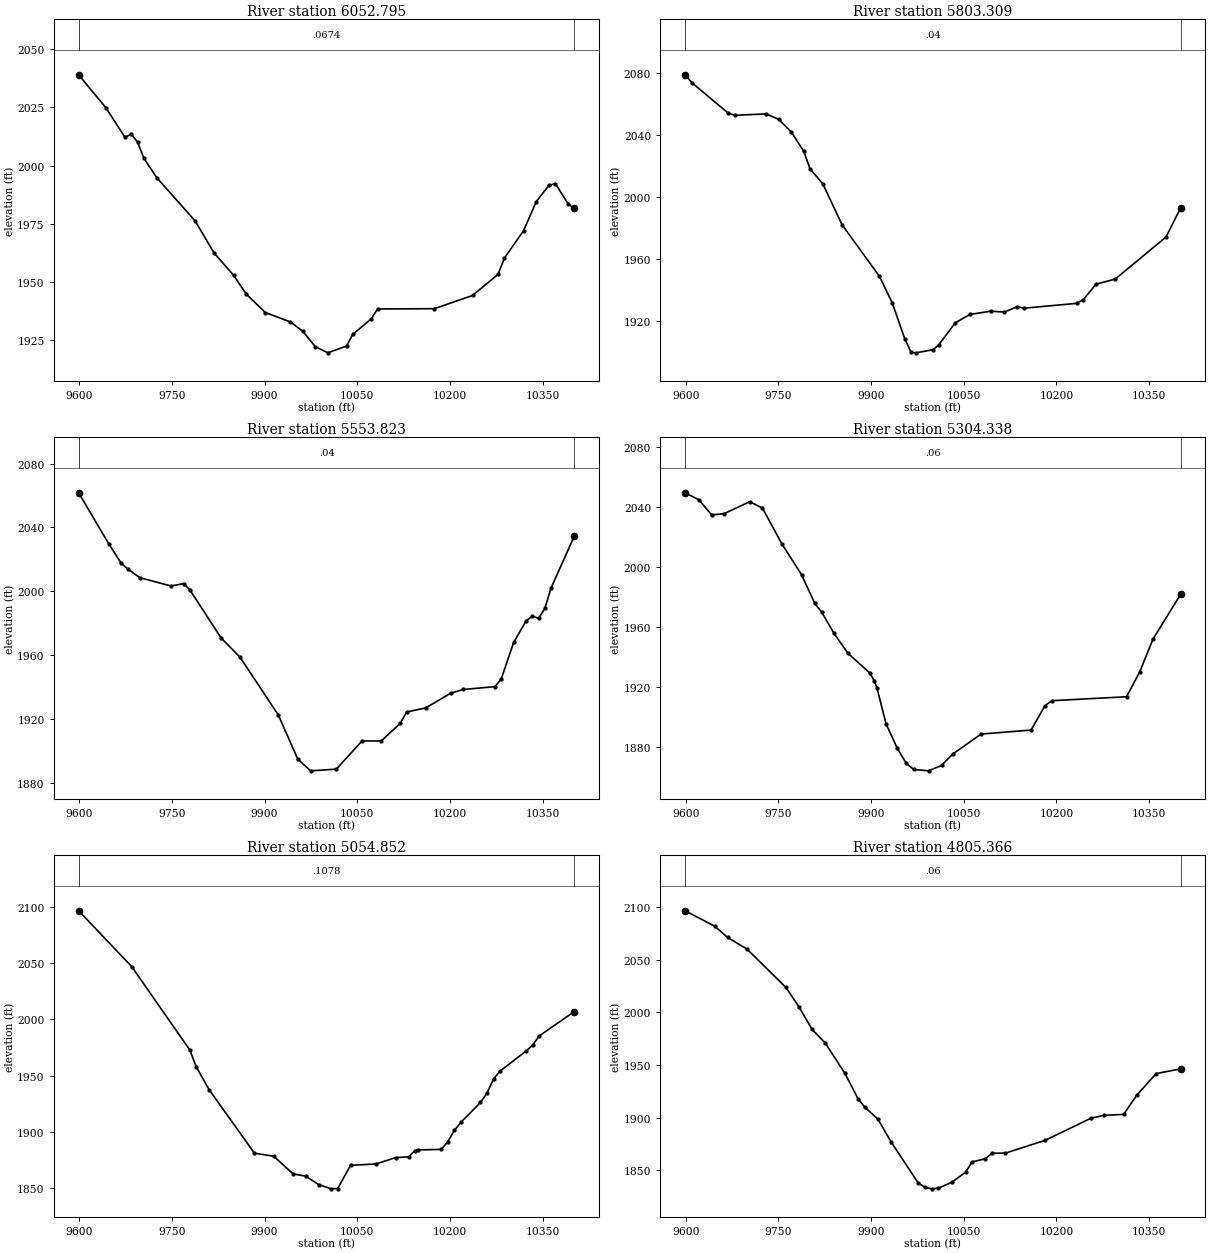
Type RM Length L Ch R = 1 ,6052.795,249.485700,249.485700,249.485700
XS GIS Cut Line= 6
562209.276352512772731.979194301562287.111558716773043.341335061
562291.651449542773085.175809568562283.455810272773156.921989607
562287.202455038773209.350912595562360.755503795773514.396231401
#Sta/Elev= 30
9599.0932039.063 9643.212024.8789673.9762012.1769684.2312013.4819694.4862010.077
9704.7412003.105 9725.45 1994.789787.5911976.1639818.6611962.2089849.7321952.809
9870.4451944.6219901.263  1936.79941.8811932.6549961.9981928.5889982.0281922.031
 10002.31919.36310032.55 1922.3110042.561927.29110072.651934.00410082.71 1938.25
10174.631938.36710236.521944.05810277.781953.166 10288.11960.16810319.041971.956
10339.681984.50510360.311991.53710370.621992.17710391.251983.45510400.941981.574
#Mann= 3 , 0 , 0
9599.093  0.0674       09599.093  0.0674       010400.94  0.0674       0
#XS Ineff= 2 , 0
       0                               0
Bank Sta=9599.093,10400.94
Exp/Cntr=0.3,0.1

Type RM Length L Ch R = 1 ,5803.309,249.485700,249.485700,249.485700
XS GIS Cut Line= 6
561958.685831473772823.993964298561969.124722903772975.714430304
561988.853289397773067.459422884 562017.86717833773136.428630284
562124.764567043773322.791676229562197.164867002773578.112041823
#Sta/Elev= 30
9599.0792078.6959610.0942073.583 9669.182053.9259680.1932052.6379730.4022053.522
9750.4862049.9979770.7542041.9679791.0292029.5169801.2952018.1789821.9442008.527
 9853.171982.1559913.3711949.1719934.3321931.8999954.4231909.0119964.8911900.069
9972.6851899.82810000.721901.888 10009.51904.95910036.121919.10610060.091924.522
10093.681926.63210115.671926.03510135.871929.45810148.251928.57110232.881931.662
10243.351934.01210264.081944.011 10295.1 1947.2710377.271974.32210400.951993.067
#Mann= 3 , 0 , 0
9599.079    0.04       09599.079    0.04       010400.95    0.04       0
#XS Ineff= 2 , 0
       0                               0
Bank Sta=9599.079,10400.95
Exp/Cntr=0.3,0.1

Type RM Length L Ch R = 1 ,5553.823,249.485600,249.485600,249.485600
XS GIS Cut Line= 6
561901.108955169772876.091108578561889.895660388773003.186712605
561875.213073967773105.226819886561789.785152033773426.307774613
561767.594996781773544.856248579561751.701930785773662.029957884
#Sta/Elev= 30
9599.0562061.7179648.1552029.4879668.2322017.3939678.2712013.9829698.3492008.422
9748.6832003.2639768.8892004.7569778.9922000.8999829.5071970.6969860.2491958.599
9922.2561922.3249953.5691894.7789974.4451887.34510016.111888.41610057.671906.103
10088.651906.03110119.561917.17910129.861924.21710160.761926.83110201.471936.068
10221.821938.36710272.691940.15410282.861944.86410303.041967.87510323.231981.396
10333.321984.41310343.411982.898 10353.51989.18610363.592002.02910400.962034.357
#Mann= 3 , 0 , 0
9599.056    0.04       09599.056    0.04       010400.96    0.04       0
#XS Ineff= 2 , 0
       0                               0
Bank Sta=9599.056,10400.96
Exp/Cntr=0.3,0.1

Type RM Length L Ch R = 1 ,5304.338,249.485700,249.485700,249.485700
XS GIS Cut Line= 6
 561792.16891622 772742.90148536561764.148486941772867.081893787
561722.973751395772978.327275873561555.174813738773250.248423899
 561507.88944169773349.272204928 561462.61867691773467.056073292
#Sta/Elev= 30
9599.0622049.5549621.6012044.828    96422034.7789662.3992035.6429703.6122043.595
9724.2592039.314 9755.822015.3539787.4251994.8999808.9341975.6619819.7931970.107
9839.9241955.7729862.8261942.3059897.8341929.3129904.8551924.2329909.3831919.464
9924.3671895.1669942.3691879.0129957.0471868.8659969.0741864.8469993.1261863.931
 10014.21867.57810031.871875.05810077.941888.45910158.921891.15810181.51 1907.48
10192.721910.76510313.381913.39210334.851930.05510356.151951.85110400.95 1981.79
#Mann= 3 , 0 , 0
9599.062    0.06       09599.062    0.06       010400.95    0.06       0
#XS Ineff= 2 , 0
       0                               0
Bank Sta=9599.062,10400.95
Exp/Cntr=0.3,0.1

Type RM Length L Ch R = 1 ,5054.852,249.485700,249.485700,249.485700
XS GIS Cut Line= 6
561519.177447507772652.389434397561491.974923074772748.713935538
 561427.13998325772959.911586774561406.772710797773038.276777507
 561381.82158081773130.504774235561283.097592998773418.473813597
#Sta/Elev= 30
9599.0142096.7579684.8552047.1319778.9061972.8079789.3661957.8299810.2871937.364
9883.5121880.9269914.8931878.1549945.9551862.5199966.621 1860.399987.2871852.982
10007.961849.15610018.321849.45710039.04 1870.0410080.48 1871.3510111.871876.953
10133.011877.62910143.581883.29510148.411883.77710185.87 1884.2910196.441891.127
10207.011901.11110217.581908.36910249.29 1926.0410259.87 1934.3710270.441946.915
10281.011954.02510323.291971.90810333.861977.22110344.441985.31310400.972006.924
#Mann= 3 , 0 , 0
9599.014  0.1078       09599.014  0.1078       010400.97  0.1078       0
#XS Ineff= 2 , 0
       0                               0
Bank Sta=9599.014,10400.97
Exp/Cntr=0.3,0.1

Type RM Length L Ch R = 1 ,4805.366,249.485700,249.485700,249.485700
XS GIS Cut Line= 6
561310.378634188772568.951472175561239.330013478772792.994431646
561199.546024468772896.682403411561158.429793551772988.250110609
 561118.03525564773089.826593964561038.953834874773322.828857982
#Sta/Elev= 30
9599.043 2096.369647.0512081.6889667.903 2071.05 9699.182060.0129762.3792023.584
9783.4822005.0199804.5851983.7859825.6881971.0359857.6931942.0869879.1151917.885
9889.8261910.0929911.2471898.5899932.6691876.8589976.1191838.3349987.0441834.129
9997.9691832.58510009.021833.175   100311838.98110052.831848.27510063.591858.134
10085.11 1861.1710095.881866.382 10117.41866.47210181.621878.59310255.981899.613
10277.191902.348 10308.71903.18810329.711921.21310361.231941.90710400.971946.374
#Mann= 3 , 0 , 0
9599.043    0.06       09599.043    0.06       010400.97    0.06       0
#XS Ineff= 2 , 0
       0                               0
Bank Sta=9599.043,10400.97
Exp/Cntr=0.3,0.1

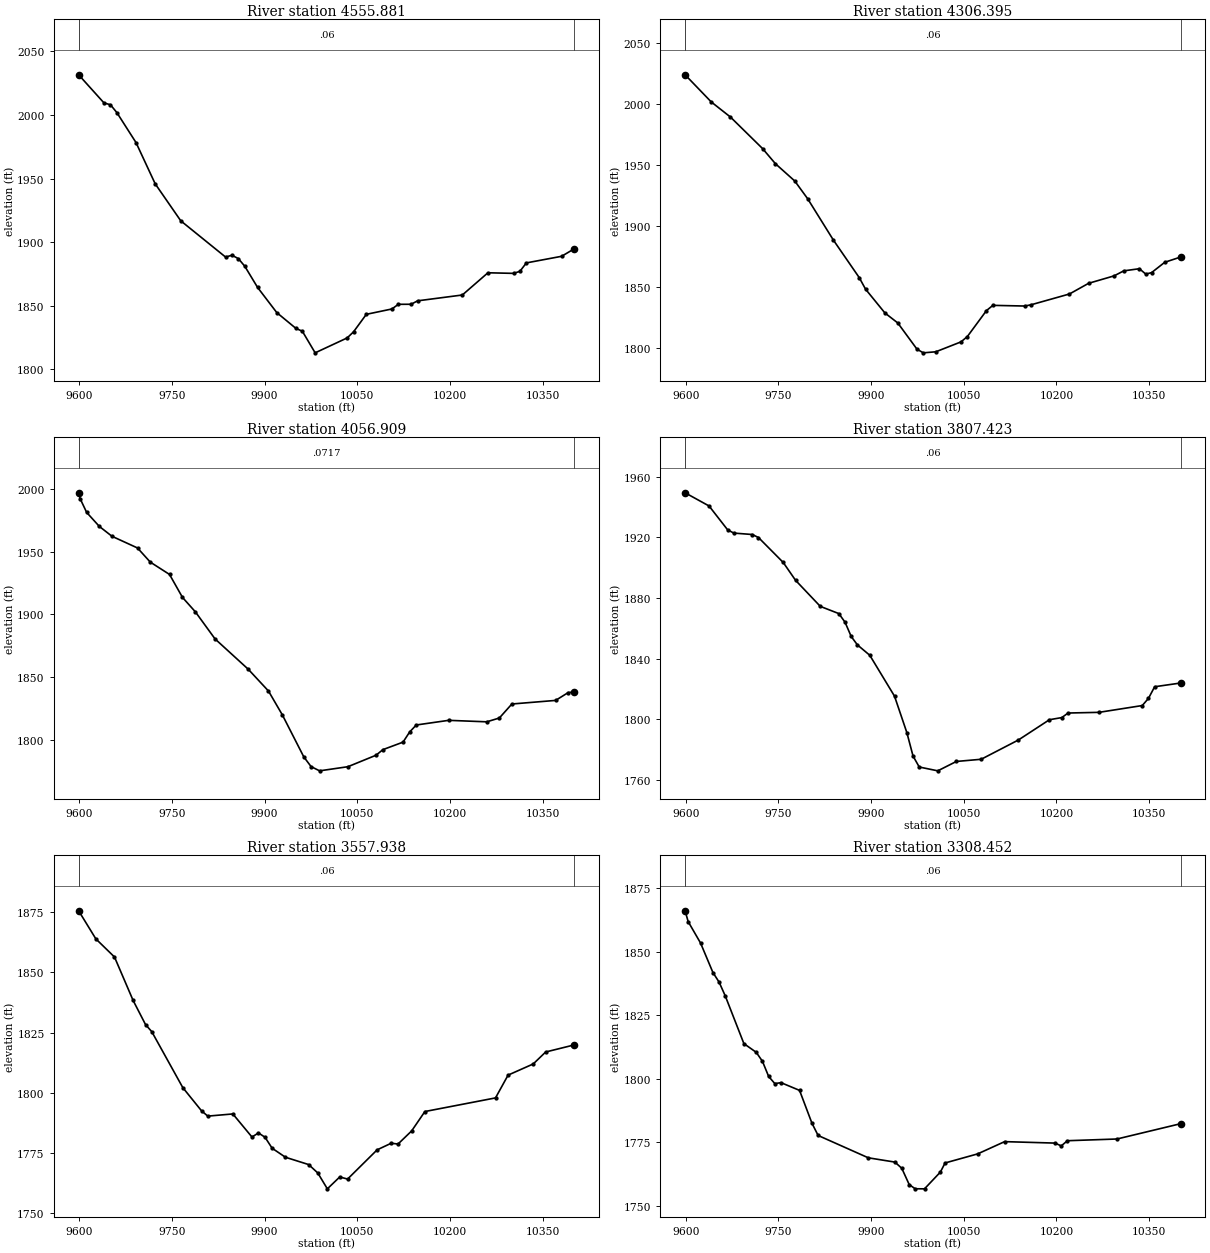
Type RM Length L Ch R = 1 ,4555.881,249.485700,249.485700,249.485700
XS GIS Cut Line= 4
561048.095706027772475.314892659560944.381186948772861.625737541
560943.979998501772863.585086369560839.691027567773249.742114353
#Sta/Elev= 30
9599.0092031.5059640.0992009.3639650.454 2007.979660.8082001.854 9691.871978.247
9722.9321945.8369764.3491916.7569836.8281888.3029847.1821889.7379857.5361887.068
 9867.891881.1069888.5981864.4649919.6611844.6839950.7231832.2389961.077 1830.03
9981.7861813.05510033.541824.757 10043.91829.54110064.621843.31310106.051847.522
10116.411851.17910137.121851.21710147.481853.90610219.991858.49610261.421875.953
10302.861875.48710313.211877.09910323.571883.70810380.631888.89610400.991894.751
#Mann= 3 , 0 , 0
9599.009    0.06       09599.009    0.06       010400.99    0.06       0
#XS Ineff= 2 , 0
       0                               0
Bank Sta=9599.009,10400.99
Exp/Cntr=0.3,0.1

Type RM Length L Ch R = 1 ,4306.395,249.485700,249.485700,249.485700
XS GIS Cut Line= 6
560805.739539699 772434.16597427560774.640989432772547.067100223
 560707.58733291772775.737989069560689.918875744772865.094720246
560632.858056675  773085.8987577560604.525277935773210.058358661
#Sta/Elev= 30
9599.0242024.1669641.3792001.8939672.4961989.4939724.397 1963.689745.2391951.251
9776.5021937.0989797.3441922.5799839.0281888.6539880.7121858.0019891.1341848.391
9922.3971828.9389943.2391820.7329974.2151799.3049984.4711796.25310004.731797.115
10045.461805.22510055.781809.59710086.771830.905 10097.11835.17210148.741834.618
10159.071835.66710221.041844.49310252.031853.246 10293.2 1859.3310308.931863.453
10334.231865.20710344.491860.80510353.881861.98410375.261870.48210400.961874.787
#Mann= 3 , 0 , 0
9599.024    0.06       09599.024    0.06       010400.96    0.06       0
#XS Ineff= 2 , 0
       0                               0
Bank Sta=9599.024,10400.96
Exp/Cntr=0.3,0.1

Type RM Length L Ch R = 1 ,4056.909,249.485600,249.485600,249.485600
XS GIS Cut Line= 6
560617.523477402 772332.36935789560543.531857707772585.910747906
560444.331272901772762.326164592560409.739662016772843.829210131
560380.468364413772958.808796744560362.411639065773084.851047529
#Sta/Elev= 30
9599.0531997.028 9601.751992.0419612.0021981.3869632.5071970.2049653.012 1962.31
9694.3391952.9739715.0261941.6799746.1331931.8479767.098 1913.539788.0631901.939
9819.8161880.3769873.4221856.2459906.2371838.8169928.7561819.7129963.3821786.268
9975.2041778.4889988.9711775.09910034.791778.396 10080.31787.55910091.381792.011
   101241798.00710134.711806.10610145.411811.68710197.831815.40710259.441814.221
10279.861817.26110300.131828.44510370.851831.30610391.011837.48710400.941838.157
#Mann= 3 , 0 , 0
9599.053  0.0717       09599.053  0.0717       010400.94  0.0717       0
#XS Ineff= 2 , 0
       0                               0
Bank Sta=9599.053,10400.94
Exp/Cntr=0.3,0.1

Type RM Length L Ch R = 1 ,3807.423,249.485700,249.485700,249.485700
XS GIS Cut Line= 6
560229.561267966772256.228136461560231.379961811772452.342448636
 560239.94656349772683.208217427560258.152862818 772882.51299611
560262.131842496772956.986745419560264.629832924773057.046469447
#Sta/Elev= 30
9599.0141949.4939637.7881940.7859667.789 1925.07 9677.79  1922.99707.7911921.956
9717.7911919.9599757.7931903.5269777.7941891.7339817.8111874.5349847.8331869.773
 9857.841864.0989867.8481854.6689877.8551849.126 9897.871842.2829937.8991815.309
9957.913 1791.229967.9211775.7679977.9281768.54210007.951766.015   100381772.206
10078.171773.64910138.421786.37510188.631799.74710208.711801.16210218.751804.165
10268.851804.614 10338.91809.10310348.91 1813.8510358.911821.50210400.971823.969
#Mann= 3 , 0 , 0
9599.014    0.06       09599.014    0.06       010400.97    0.06       0
#XS Ineff= 2 , 0
       0                               0
Bank Sta=9599.014,10400.97
Exp/Cntr=0.3,0.1

Type RM Length L Ch R = 1 ,3557.938,249.485700,249.485700,249.485700
XS GIS Cut Line= 6
559918.493623584772367.257979727 559955.87958183772648.760933711
559980.594204442772705.103571799560087.952541032772867.641881268
560120.098527751772970.570003856560143.800240389773120.761971636
#Sta/Elev= 30
9599.0941875.5349626.9741863.8779657.1231856.3589687.2721838.3369707.3711828.327
9717.4211825.4089767.6691802.1859797.9391792.5789808.0661790.3779848.6231791.277
9879.5551781.7119890.0651783.3999900.6951781.6079912.175 1777.069933.7341773.316
9971.3251770.2799986.0671766.79610001.521760.21710021.581765.14410034.271764.271
10082.091776.39110104.871779.131 10115.91778.79910137.951784.24510159.341792.279
10273.631797.92910293.981807.38310334.631812.00710354.791816.971 10400.91819.903
#Mann= 3 , 0 , 0
9599.094    0.06       09599.094    0.06       0 10400.9    0.06       0
#XS Ineff= 2 , 0
       0                               0
Bank Sta=9599.094,10400.9
Exp/Cntr=0.3,0.1

Type RM Length L Ch R = 1 ,3308.452,249.485700,249.485700,249.485700
XS GIS Cut Line= 6
559853.662692789772370.077787037559851.046420824772653.454420341
 559826.88677794772715.242606713559752.378059208 772821.37340339
559726.820627897772907.621654363559738.267617585773137.233127417
#Sta/Elev= 30
9599.1471866.194 9604.081861.9489624.1221853.5179644.1651841.8949654.1861838.102
9664.2071832.6449694.2711813.9129714.293 1810.489724.2951806.9499734.2981801.004
9744.3011798.1819754.3031798.5529784.3231795.5069804.3411782.609 9814.351777.765
9895.5531768.9729938.573 1767.299949.7111764.8519961.7221758.4369971.3531756.788
9986.4671756.76110012.151763.35510019.761766.94610072.511770.51910116.11 1775.34
10197.651774.76510207.671773.655 10217.7  1775.710297.831776.37510400.85  1782.4
#Mann= 3 , 0 , 0
9599.147    0.06       09599.147    0.06       010400.85    0.06       0
#XS Ineff= 2 , 0
       0                               0
Bank Sta=9599.147,10400.85
Exp/Cntr=0.3,0.1

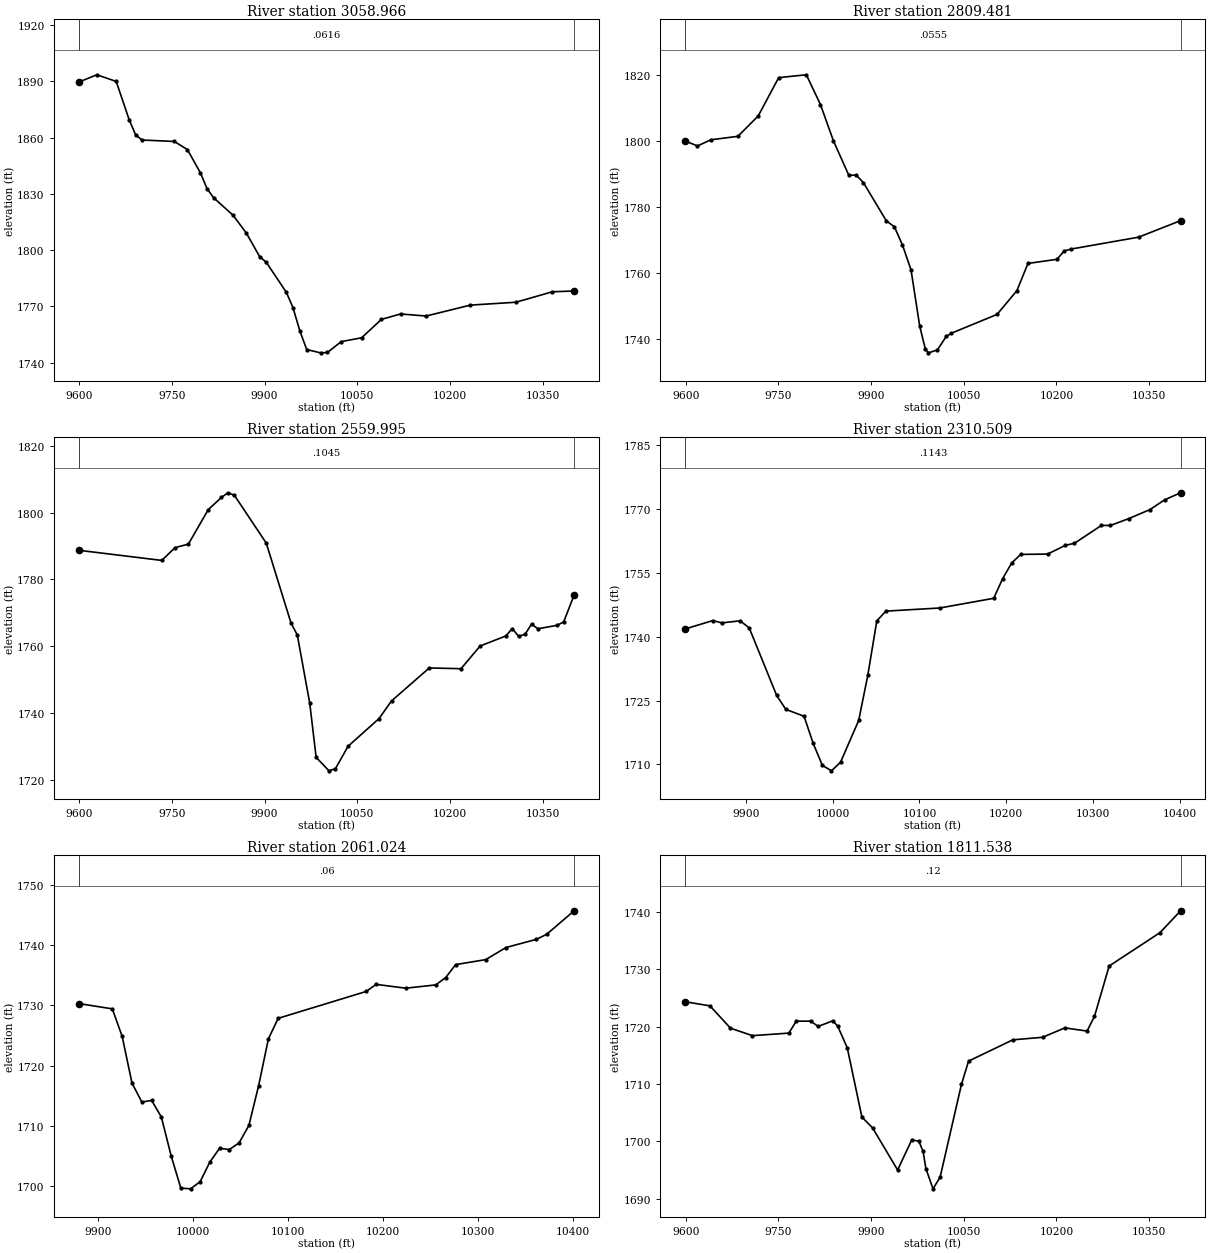
Type RM Length L Ch R = 1 ,3058.966,249.485700,249.485700,249.485700
XS GIS Cut Line= 6
559436.513241697 772346.71900754559516.068077198772597.297305339
559548.042116598 772675.95052947 559593.63084435772768.454594736
 559609.71121209772812.086808178559673.869543062773109.600792845
#Sta/Elev= 30
9599.0421889.5789628.5651893.5049659.8821889.952 9680.761869.5839691.1991861.511
9701.6381858.7359753.9411857.9629775.0661853.623 9796.191841.1879806.7521832.865
9817.3141828.0059849.0011818.5989870.304  1809.29891.8941796.6149902.6891793.548
9935.0731777.6239945.8671769.4149956.9871757.034 9968.141747.0429990.4471745.285
10001.631745.471 10023.91751.253   100571753.31910088.971763.11810120.151766.009
 10161.41764.90710232.941770.728 10306.61772.25410365.621777.83310400.931778.248
#Mann= 3 , 0 , 0
9599.042  0.0616       09599.042  0.0616       010400.93  0.0616       0
#XS Ineff= 2 , 0
       0                               0
Bank Sta=9599.042,10400.93
Exp/Cntr=0.3,0.1

Type RM Length L Ch R = 1 ,2809.481,249.485700,249.485700,249.485700
XS GIS Cut Line= 6
559172.869153819772526.620945471559240.507919822 772678.13686576
559298.167729567772781.927617144  559440.7587125772939.225374437
 559493.21493055773013.048242164 559576.79295824773209.321560683
#Sta/Elev= 30
9599.0591800.0419619.0761798.5189640.8581800.3879684.4231801.4339717.3561807.624
9750.4951819.2599795.2881820.1289818.0731811.0979839.0481800.0929864.0131789.591
9875.7011789.6829887.5751787.3919924.7271775.7679937.7741773.967 9950.821768.418
9964.6381760.8999978.7531743.7419987.9621736.7669992.8681735.68710007.211736.561
10021.66 1740.6510029.741741.62710103.851747.35610136.121754.60810153.841762.833
10200.841764.09210212.28 1766.5910223.711767.206 10332.91770.81310400.941775.837
#Mann= 3 , 0 , 0
9599.059  0.0555       09599.059  0.0555       010400.94  0.0555       0
#XS Ineff= 2 , 0
       0                               0
Bank Sta=9599.059,10400.94
Exp/Cntr=0.3,0.1

Type RM Length L Ch R = 1 ,2559.995,249.485600,249.485600,249.485600
XS GIS Cut Line= 6
559077.351728798772560.146912894559179.653227299772836.655957589
559184.248228691772892.246571886559165.823788319772974.383492023
559167.965991026773033.480986435559242.322705617773331.272331508
#Sta/Elev= 30
9599.108 1788.719733.6021785.6689755.1461789.496 9776.691790.5579808.8441800.876
9830.0291804.5089840.622 1805.929851.1081805.1729902.6641790.8729942.8721766.866
9952.901 1763.37  9973.11742.8719983.3961726.71910004.22 1722.6710014.671723.327
10035.091730.03310085.21 1738.32 10105.41743.60410166.491753.47710217.81 1753.25
10248.851760.05210290.24 1763.0410300.661765.25110311.071762.94710321.491763.567
 10331.91766.57810342.321765.20610373.561766.24710383.981767.27410400.931775.354
#Mann= 3 , 0 , 0
9599.108  0.1045       09599.108  0.1045       010400.93  0.1045       0
#XS Ineff= 2 , 0
       0                               0
Bank Sta=9599.108,10400.93
Exp/Cntr=0.3,0.1

Type RM Length L Ch R = 1 ,2310.509,249.485700,249.485700,249.485700
XS GIS Cut Line= 6
 558904.78099747772874.702654579558957.280724848773035.356333665
558967.796064759773069.242381193558987.444428482773138.085892627
 559036.86244766 773326.42878825559064.909566984773422.621804578
#Sta/Elev= 30
9829.9861741.784 9861.861743.751 9872.381743.2169893.4211743.7029903.9411742.009
9935.5031726.1899946.0231722.9259967.0641721.3029977.5841714.9539988.1051709.799
9998.6251708.49810009.091710.51210030.041720.33410040.471730.87210050.871743.668
10061.271745.97310123.561746.71110185.591748.98110195.931753.60710206.271757.252
10216.611759.28110247.621759.357 10268.31761.41710278.641761.89110309.721766.083
10320.141766.07510340.971767.66110365.591769.79510382.631772.09510400.991773.741
#Mann= 3 , 0 , 0
9829.986  0.1143       09829.986  0.1143       010400.99  0.1143       0
#XS Ineff= 2 , 0
       0                               0
Bank Sta=9829.986,10400.99
Exp/Cntr=0.3,0.1

Type RM Length L Ch R = 1 ,2061.024,249.485700,249.485700,249.485700
XS GIS Cut Line= 6
558681.918958727772940.826556193558700.710944135773009.091295302
558714.906395713773077.348624393 558759.04507029773257.947079972
558787.910319402773348.510917299558823.278224443 773442.14014418
#Sta/Elev= 30
9879.368 1730.329914.8121729.4369925.1841724.8599935.5561717.0569945.9281713.917
9956.2181714.1889966.4511711.4229976.684    17059986.918 1699.599997.1511699.465
10007.331700.66510017.511703.92810027.761706.21910038.031705.999 10048.31707.127
10058.571710.01710068.851716.66510079.121724.44110089.391727.859 10182.11732.336
10192.441733.51410223.721732.87710255.211733.42410265.71 1734.64 10276.21736.803
10307.821737.63410329.191739.64910361.261741.01410371.951741.84310400.971745.768
#Mann= 3 , 0 , 0
9879.368    0.06       09879.368    0.06       010400.97    0.06       0
#XS Ineff= 2 , 0
       0                               0
Bank Sta=9879.368,10400.97
Exp/Cntr=0.3,0.1

Type RM Length L Ch R = 1 ,1811.538,249.485700,249.485700,249.485700
XS GIS Cut Line= 6
558273.573206325772812.796942487558434.526258326773068.827539912
558483.250077138773155.650936009558515.479079522773212.393304537
558630.313104274 773385.05607393558696.990396127773493.556484113
#Sta/Elev= 30
 9599.021724.3249639.2791723.6049672.4931719.7189707.9291718.4169766.9881718.859
  9778.81720.9399802.4241720.9459814.2351720.0199837.8591720.9969845.9621720.087
9861.4831716.2879885.1061704.2399902.4071702.3559942.9211695.0179965.8571700.264
9977.3251700.0269984.1241698.2669988.7921695.23210000.261691.73310011.751693.774
10046.25 1709.9210057.751713.98210129.441717.68910177.47 1718.13 10213.51719.769
10249.531719.21610261.541721.77110285.291730.54710367.451736.35210400.971740.168
#Mann= 3 , 0 , 0
 9599.02    0.12       0 9599.02    0.12       010400.97    0.12       0
#XS Ineff= 2 , 0
       0                               0
Bank Sta=9599.02,10400.97
Exp/Cntr=0.3,0.1

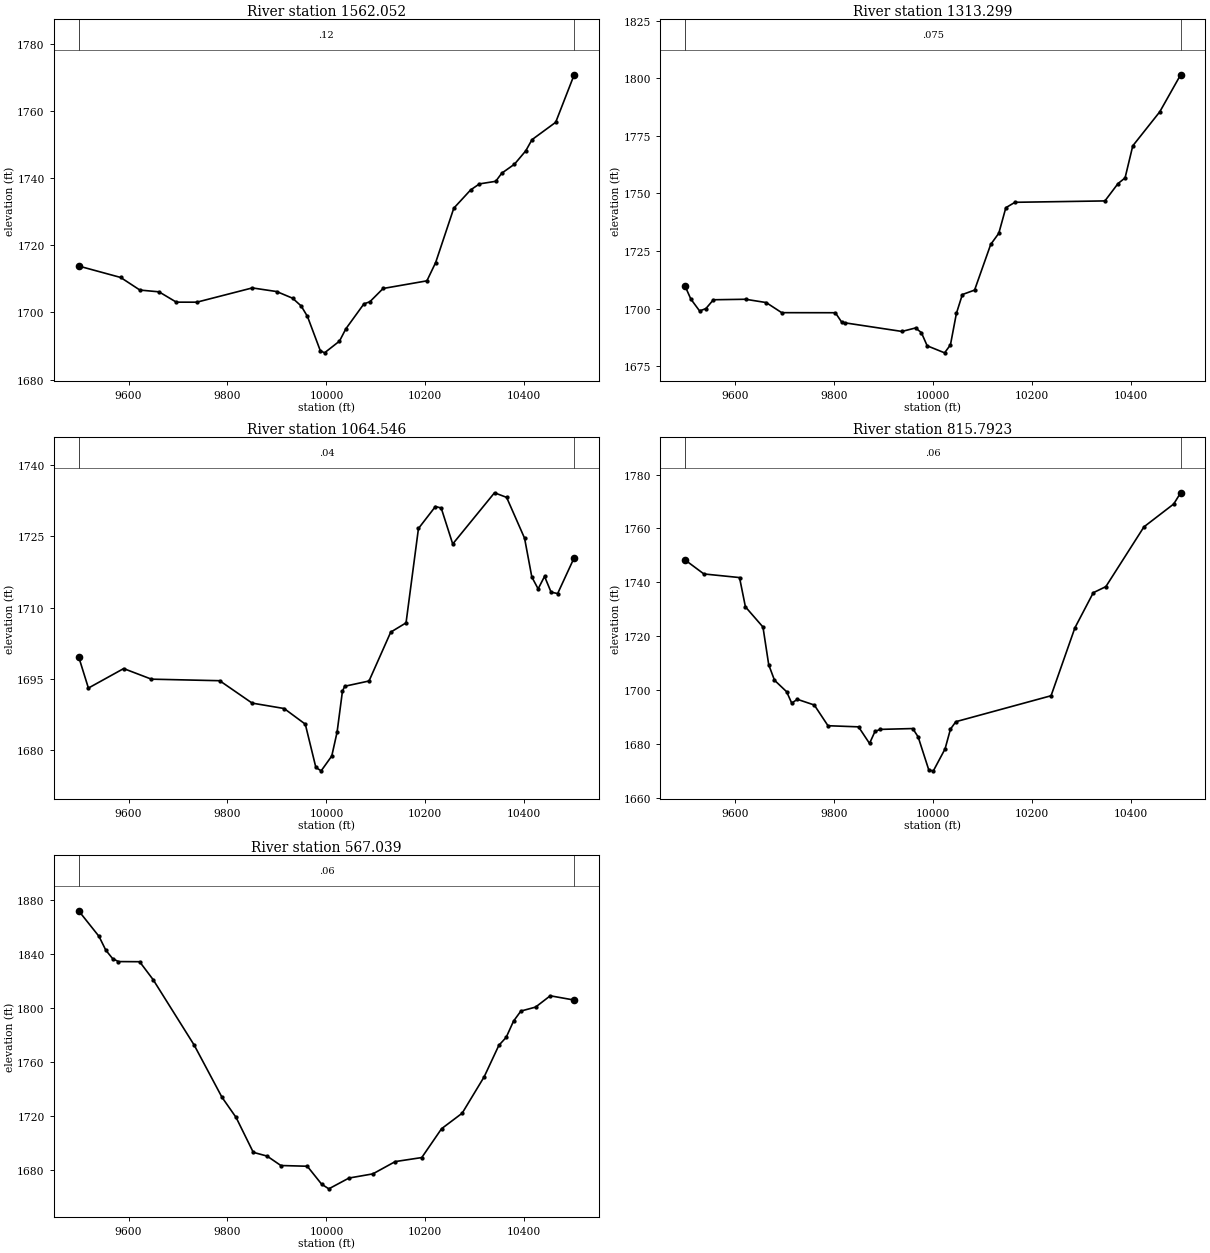
Type RM Length L Ch R = 1 ,1562.052,248.753300,248.753300,248.753300
XS GIS Cut Line= 6
557930.222154976773028.788554717558084.163734215773156.590227164
 558159.64575278773214.377934819558289.428427867773308.392458747
558356.685593607773363.678957337558735.856559741773623.174410735
#Sta/Elev= 30
9499.0291713.7819583.9871710.3769622.9121706.6259661.5541706.0989696.5961703.025
9737.9541703.0169850.1861707.2649899.5781706.179 9931.611704.202 9948.971701.896
9961.6631698.7829987.5961688.6069996.2371687.93910026.441691.42510039.331695.092
10075.821702.50610087.93 1703.1510114.671707.096 10203.21709.37110220.911714.819
10257.581730.99610291.731736.44910309.441738.227 10342.41739.00110354.521741.409
10380.261744.09310402.99 1748.0510415.671751.38910463.581756.56110500.971770.708
#Mann= 3 , 0 , 0
9499.029    0.12       09499.029    0.12       010500.97    0.12       0
#XS Ineff= 2 , 0
       0                               0
Bank Sta=9499.029,10500.97
Exp/Cntr=0.3,0.1

Type RM Length L Ch R = 1 ,1313.299,248.753400,248.753400,248.753400
XS GIS Cut Line= 6
 557857.40333402773132.877359669558088.798262629773408.685693896
558206.871890398773584.453593254558270.036439989773666.097188295
558373.439151551773782.016012399558495.614326697773902.170474817
#Sta/Elev= 30
9499.0441709.7189510.6161704.1269528.3721698.9489541.0811699.9759556.3131703.812
9621.1691704.0269662.9411702.5999694.4171698.199 9802.851698.172 9815.731694.067
9821.3551693.8099937.4731690.0399964.9581691.5569976.7321689.5349988.5051683.804
 10023.71680.74210035.531684.20310047.571697.86610059.611706.07510084.331708.009
10116.961727.867 10133.31732.70910147.541743.81610165.991746.16710347.861746.769
10374.391754.318 10388.61756.771 10404.21770.71310458.821785.51510500.961801.589
#Mann= 3 , 0 , 0
9499.044   0.075       09499.044   0.075       010500.96   0.075       0
#XS Ineff= 2 , 0
       0                               0
Bank Sta=9499.044,10500.96
Exp/Cntr=0.3,0.1

Type RM Length L Ch R = 1 ,1064.546,248.753300,248.753300,248.753300
XS GIS Cut Line= 6
557723.624270042773200.968539198557799.949207853773314.829737552
557866.035363923773435.419707767558034.878010343773831.064649063
558120.322781181773962.250532564558209.554029727774070.198227497
#Sta/Elev= 30
9499.0431699.6719518.7961693.0679590.0891697.1679646.182 1694.949784.1841694.615
9849.8471689.9029914.5251688.7649957.3141685.4739978.7091676.3599989.4061675.652
10010.851678.77410021.611683.80410032.371692.356 10036.91693.44310086.161694.555
10130.051704.83510161.011706.78510186.111726.64110220.441731.26710232.091730.949
10255.391723.38210339.861734.15410364.351733.18710400.661724.59210415.321716.434
10428.071713.93510441.031716.56210454.281713.24510467.541712.95110500.941720.486
#Mann= 3 , 0 , 0
9499.043    0.04       09499.043    0.04       010500.94    0.04       0
#XS Ineff= 2 , 0
       0                               0
Bank Sta=9499.043,10500.94
Exp/Cntr=0.3,0.1

Type RM Length L Ch R = 1 ,815.7923,248.753300,248.753300,248.753300
XS GIS Cut Line= 6
557473.298343974773273.911093315557621.076469532773511.378480343
557751.599185124773800.853006294557803.051567493773897.207222342
 557873.11053979773999.415808822557984.270884595774129.508036699
#Sta/Elev= 30
9499.0311748.2789536.9961743.0889609.0841741.7469620.9931730.8739656.4661723.376
9668.1251709.3429679.7841703.6089704.2731699.348 9714.581695.1199725.996 1696.52
9760.2441694.4049787.9141686.7129849.6871686.2949871.9261680.1339883.0461684.614
9893.9841685.3559959.279 1685.669970.1621682.5919991.9261670.185   100011669.954
10024.651678.10110035.561685.45210046.481688.21110238.971697.84810287.171723.076
10324.311736.11610349.751738.37810426.79 1760.58   104871769.07710500.951773.238
#Mann= 3 , 0 , 0
9499.031    0.06       09499.031    0.06       010500.95    0.06       0
#XS Ineff= 2 , 0
       0                               0
Bank Sta=9499.031,10500.95
Exp/Cntr=0.3,0.1

Type RM Length L Ch R = 1 , 567.039,0.000000,0.000000,0.000000
XS GIS Cut Line= 6
557160.122650739773494.875536051557293.537989985773637.737867345
 557438.20720578773781.603215127557551.808464939773889.127198391
557696.944197306 774017.72771209557883.286636356774187.587798625
#Sta/Elev= 30
9499.0111872.2949540.2281853.2759553.9111843.0469567.5941836.8319579.4131834.555
9622.3241834.4569649.6891821.1129732.7241772.4689788.8341733.7739817.4481718.733
9852.1341692.8589880.0711690.062 9907.911683.0629961.3681682.5189990.3331669.203
10004.871665.73210045.631673.74610093.951676.85110139.19 1685.9810192.81 1688.97
10232.891710.40910274.491721.90310319.031748.97210348.711772.33910363.561778.282
 10378.41790.33310393.251797.79510422.931800.73810452.62 1809.14   105011805.968
#Mann= 3 , 0 , 0
9499.011    0.06       09499.011    0.06       0   10501    0.06       0
#XS Ineff= 2 , 0
       0                               0
Bank Sta=9499.011,10501
Exp/Cntr=0.3,0.1